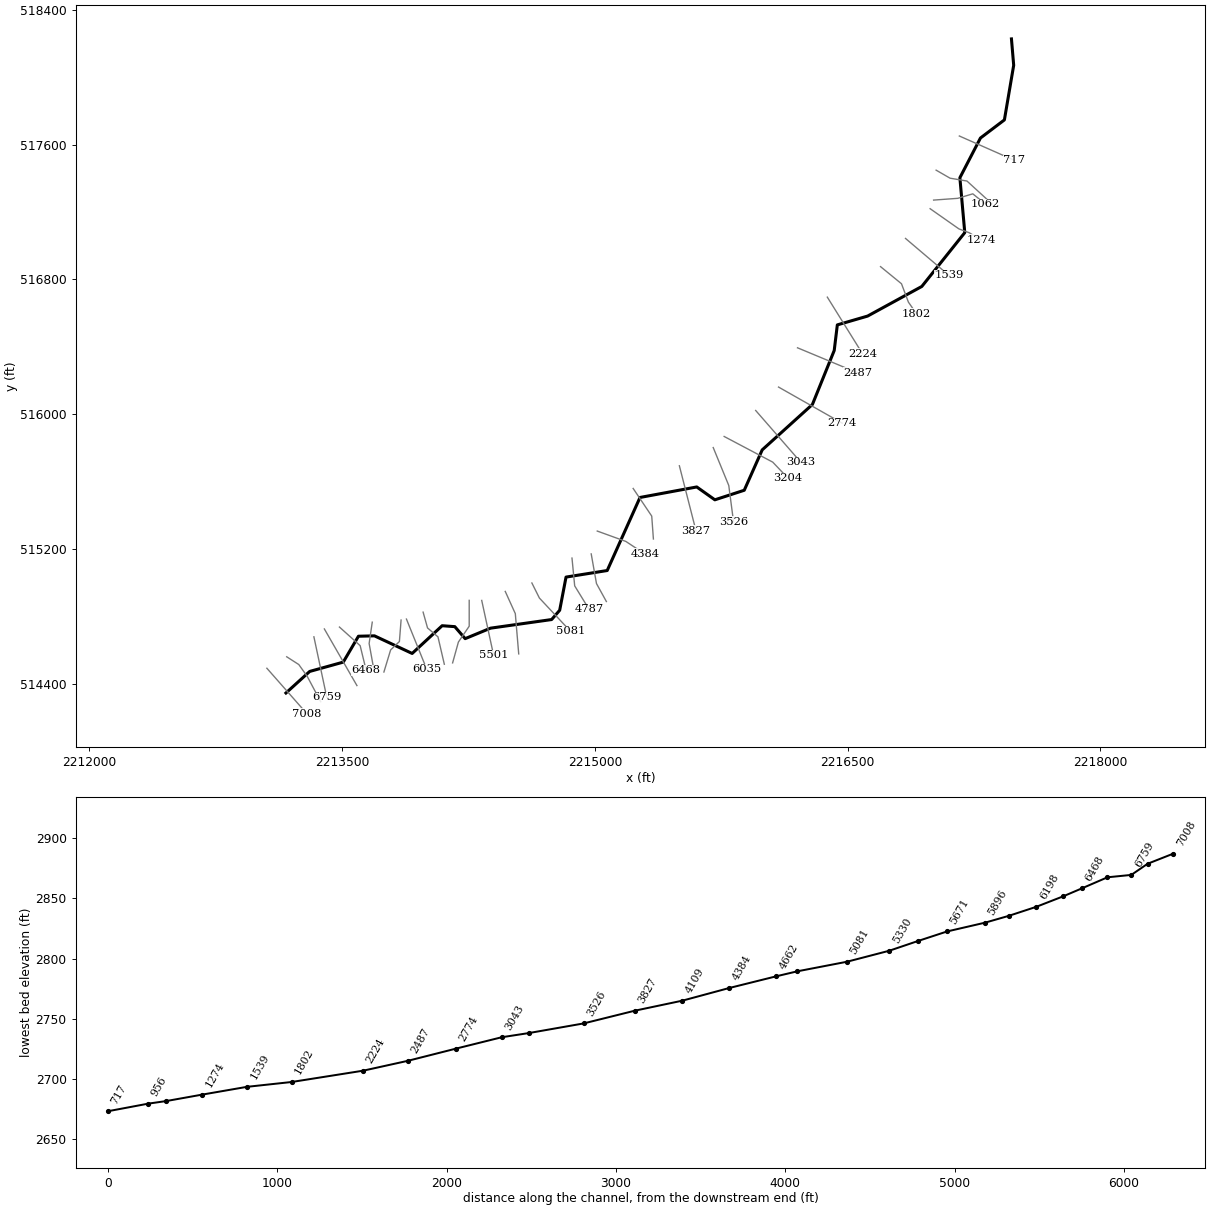
--- LAURELRN4.prj (project) ---

Proj Title=LAURELRN4
Current Plan=p01
Default Exp/Contr=0,0
English Units
Geom File=g01
Flow File=f01
Plan File=p01
Background Map Layer=Inundation Boundary (01pct Value_0)
Background Map Layer=Inundation Boundary (01pct Value_0)
Background Map Layer=Inundation Boundary (01pct Value_0)
Background Map Layer=Inundation Boundary (01pct Value_0)
Background Map Layer=Inundation Boundary (01pct Value_0)
Background Map Layer=Inundation Boundary (01pct Value_0)
BEGIN DESCRIPTION:
----------MODEL BY WOOD PLC 2021----------
Stream Name: Laurel Run IV
Flood Zone: Enhanced Approximate
Pocahontas County, WV
HEC-RAS Version: RAS 6.1
Vertical Datum: NAVD88
Projection: NAD 1983 StatePlane West Virginia S FIPS 4702 (US Feet)
Terrain: 1-meter LIDAR (FEMA Region III 3DEP collected 2016-2018)
Land Use: 2019 NLCD
Hydrologic Method:
WV SIR2010-5033 regression equations
Model Notes:
Normal depth tie in to Old Field Fork
END DESCRIPTION:
DSS Export Rating Curves= 0
DSS Export Rating Curve Sorted= 0
DSS Export Volume Flow Curves= 0
DXF OffsetX= 0
DXF OffsetY= 0
DXF ScaleX= 0
DXF ScaleY= 0

--- LAURELRN4.p01 (plan) ---

Plan Title=Floodplain
Program Version=6.00
Short Identifier=Floodplain
Geom File=g01
Flow File=f01
Subcritical Flow
K Sum by GR= 0
Std Step Tol= 0.01
Critical Tol= 0.01
Num of Std Step Trials= 20
Max Error Tol= 0.3
Flow Tol Ratio= 0.001
Split Flow NTrial= 30
Split Flow Tol= 0.02
Split Flow Ratio= 0.02
Log Output Level= 0
Friction Slope Method= 1
Unsteady Friction Slope Method= 2
Unsteady Bridges Friction Slope Method= 1
Parabolic Critical Depth
Global Vel Dist= 0 , 0 , 0
Global Log Level= 0
CheckData=False
Encroach Param=-1 ,0,0, 0
Mapping Interval=1HOUR
Computation Time Step Use Courant=        0
Computation Time Step Use Time Series=    0
Computation Time Step Count To Double=0
Computation Time Step Max Doubling=0
Computation Time Step Max Halving=0
Computation Time Step Residence Courant=0
Run HTab= 0
Run UNet= 0
Run Sediment= 0
Run PostProcess= 0
Run WQNet= 0
Run RASMapper=-1
UNET Theta= 0
UNET Theta Warmup= 0
UNET ZTol= 0
UNET ZSATol= 0
UNET MxIter= 0
UNET Max Iter WO Improvement= 0
UNET MaxInSteps= 0
UNET DtIC= 0
UNET DtMin= 0
UNET MaxCRTS= 0
UNET WFStab= 0
UNET SFStab= 0
UNET WFX= 1
UNET SFX= 1
UNET Gravity=32.174
UNET 1D Methodology=Finite Difference
UNET DSS MLevel= 1
UNET Pardiso=0
UNET DZMax Abort= 0
UNET Use Existing IB Tables= 0
UNET Froude Reduction=False
UNET Froude Limit= 0
UNET Froude Power= 0
UNET D1 Cores= 0
UNET WindReference=Eulerian
UNET WindDragFormulation=Hsu (1988)
UNET D2 Coriolis=0
UNET D2 Cores= 0
UNET D2 Theta= 1
UNET D2 Theta Warmup= 1
UNET D2 Z Tol= 0.01
UNET D2 Volume Tol= 0.01
UNET D2 Max Iterations= 20
UNET D2 Equation= 0
UNET D2 RampUpFraction=0.1
UNET D2 TimeSlices= 1
UNET D2 Turbulence Formulation=Non-Conservative (original)
UNET D2 Eddy Viscosity=0.3
UNET D2 Transverse Eddy Viscosity=0.1
UNET D2 Smagorinsky Mixing=0
UNET D2 BCVolumeCheck=0
UNET D2 Cores=0
UNET D2 SolverType=PARDISO (Direct)
UNET D2 Minimum Iterations= 2147483647
UNET D2 Maximum Iterations= 2147483647
UNET D2 Restart Number= 10
UNET D2 Relaxation Coeff=1.3
UNET D2 SOR Precondition Iterations= 10
UNET D2 ILUT Maximum Fill= 8
UNET D2 ILUT Tolerance=1E-08
UNET D1D2 MaxIter= 0
UNET D1D2 ZTol=0.01
UNET D1D2 QTol=0.1
UNET D1D2 MinQTol=1
Write IC File= 0
Write IC File at Fixed DateTime=0
Write IC File at Sim End=0
Echo Input=False
Echo Parameters=False
Echo Output=False
Write Detailed= 0
HDF Write Warmup=0
HDF Write Time Slices=0
HDF Flush=0
HDF Compression= 1
HDF Chunk Size= 1
HDF Spatial Parts= 1
HDF Use Max Rows=0
HDF Fixed Rows= 1
Calibration Method= 0
Calibration Iterations= 20
Calibration Max Change=0.05
Calibration Tolerance=0.2
Calibration Maximum=1.5
Calibration Minimum=0.5
Calibration Optimization Method= 1
WQ AD Non Conservative
WQ ULTIMATE=-1
WQ Max Comp Step=1HOUR
WQ Output Interval=15MIN
WQ Output Selected Increments= 0
WQ Output face flow=0
WQ Output face velocity=0
WQ Output face area=0
WQ Output face dispersion=0
WQ Output cell volume=0
WQ Output cell surface area=0
WQ Output cell continuity=0
WQ Output cumulative cell continuity=0
WQ Output face conc=0
WQ Output face dconc_dx=0
WQ Output face courant=0
WQ Output face peclet=0
WQ Output face adv mass=0
WQ Output face disp mass=0
WQ Output cell mass=0
WQ Output cell source sink temp=0
WQ Output nsm pathways=0
WQ Output nsm derived pathways=0
WQ Create Restart=0
WQ Fixed Restart=0
WQ System Summary=0
WQ Write To DSS=0
Sorting and Armoring Iterations= 10
XS Update Threshold= 0.02
Bed Roughness Predictor= 0
Hydraulics Update Threshold= 0.02
Energy Slope Method= 1
Volume Change Method= 1
Sediment Retention Method= 0
Sediment TS Multiplier= 1
Warm Up Method= 0
XS Weighting Method= 0
Number of US Weighted Cross Sections= 1
Number of DS Weighted Cross Sections= 1
Upstream XS Weight=0
Main XS Weight=1
Downstream XS Weight=0
Number of DS XS's Weighted with US Boundary= 1
Upstream Boundary Weight= 1
Weight of XSs Associated with US Boundary= 0
Number of US XS's Weighted with DS Boundary= 1
Downstream Boundary Weight= 0.5
Weight of XSs Associated with DS Boundary= 0.5
Percentile Method= 0
Sediment Output Level= 3
Mass or Volume Output= 0
Output Increment Type= 1
Profile and TS Output Increment= 1
Transport Output Increment 1
XS Output Flag= 0
XS Output Increment= 10
Read HDF5 Sediment Hotstart= 0
Sediment Hotstart Type= 0
Write Gradation File= 0
Read Gradation Hotstart= 0
Write HDF5 File= 1
Write Binary Output= 1
Write DSS Sediment File= 0
DSS Sediment Output Type= 1
SV Curve= 0
Specific Gage Flag= 0
Subcell Erosion Methods= 0
Subcell Deposition Methods= 0
Advection Scheme= 1
Matrix Solver= 0
Implicit Weighting Factor= 1
Maximum Outer Loop Convergence Iterations= 5
Convergence Maximum Absolute= 0.001
Convergence RMSE= 0.0001
Grain Fractions Max Abs Error= 0.001
Max Subgrid Regions= 1
Max Subgrid Length Scale= 3.402823E+38
Initial Layer Thickness= 3.402823E+38
Min Layer Thickness= 3.402823E+38
Max Layer Thickness= 3.402823E+38
Number of Layers= 5

--- LAURELRN4.f01 (steady flow) ---

Flow Title=Flow
Program Version=6.10
Number of Profiles= 6
Profile Names=01pct,10pct,04pct,02pct,0_2pct,01plus
River Rch & RM=LAURELRN4,Main            ,7008
     616     326     433     522     859     911
River Rch & RM=LAURELRN4,Main            ,4109
     708     377     500     601     985    1050
Boundary for River Rch & Prof#=LAURELRN4,Main            , 1
Up Type= 0
Dn Type= 3
Dn Slope=0.0155
Boundary for River Rch & Prof#=LAURELRN4,Main            , 2
Up Type= 0
Dn Type= 3
Dn Slope=0.0155
Boundary for River Rch & Prof#=LAURELRN4,Main            , 3
Up Type= 0
Dn Type= 3
Dn Slope=0.0155
Boundary for River Rch & Prof#=LAURELRN4,Main            , 4
Up Type= 0
Dn Type= 3
Dn Slope=0.0155
Boundary for River Rch & Prof#=LAURELRN4,Main            , 5
Up Type= 0
Dn Type= 3
Dn Slope=0.0155
Boundary for River Rch & Prof#=LAURELRN4,Main            , 6
Up Type= 0
Dn Type= 3
Dn Slope=0.0155
DSS Import GetInterval= 0
DSS Import GetPeak= 0
DSS Import FillOption= 0

--- LAURELRN4.g01 (geometry) ---

Geom Title=Geometry
Program Version=6.10

River Reach=LAURELRN4       ,Main
Reach XY= 30
     2213167.004      514348.1662213307.96828009514475.985722745
2213507.03355884 514531.181764372213597.24826785514684.727716103
2213692.15435488514687.0084377822213915.97244039514582.622243149
     2214093.925      514747.0292214169.05187904 514741.53111161
2214230.53490087514670.3755438732214381.14425913514732.539809195
2214743.71471776514783.6170766462214791.49455911514838.790657574
2214829.13299764515035.3816563332215073.51246036515074.279482539
     2215268.134      515507.426     2215604.864      515569.746
      2215712.38      515493.511     2215886.715      515550.139
     2215993.281      515789.482     2216291.276      516058.801
     2216420.683      516378.7722216439.14084926516530.639570193
2216618.79478268516582.855533577     2216940.448      516758.474
2217195.49683372517077.614711385     2217166.422       517403.04
     2217288.438      517638.4782217430.60526424517745.951654477
2217485.76344372518069.896518058     2217472.469       518226.14

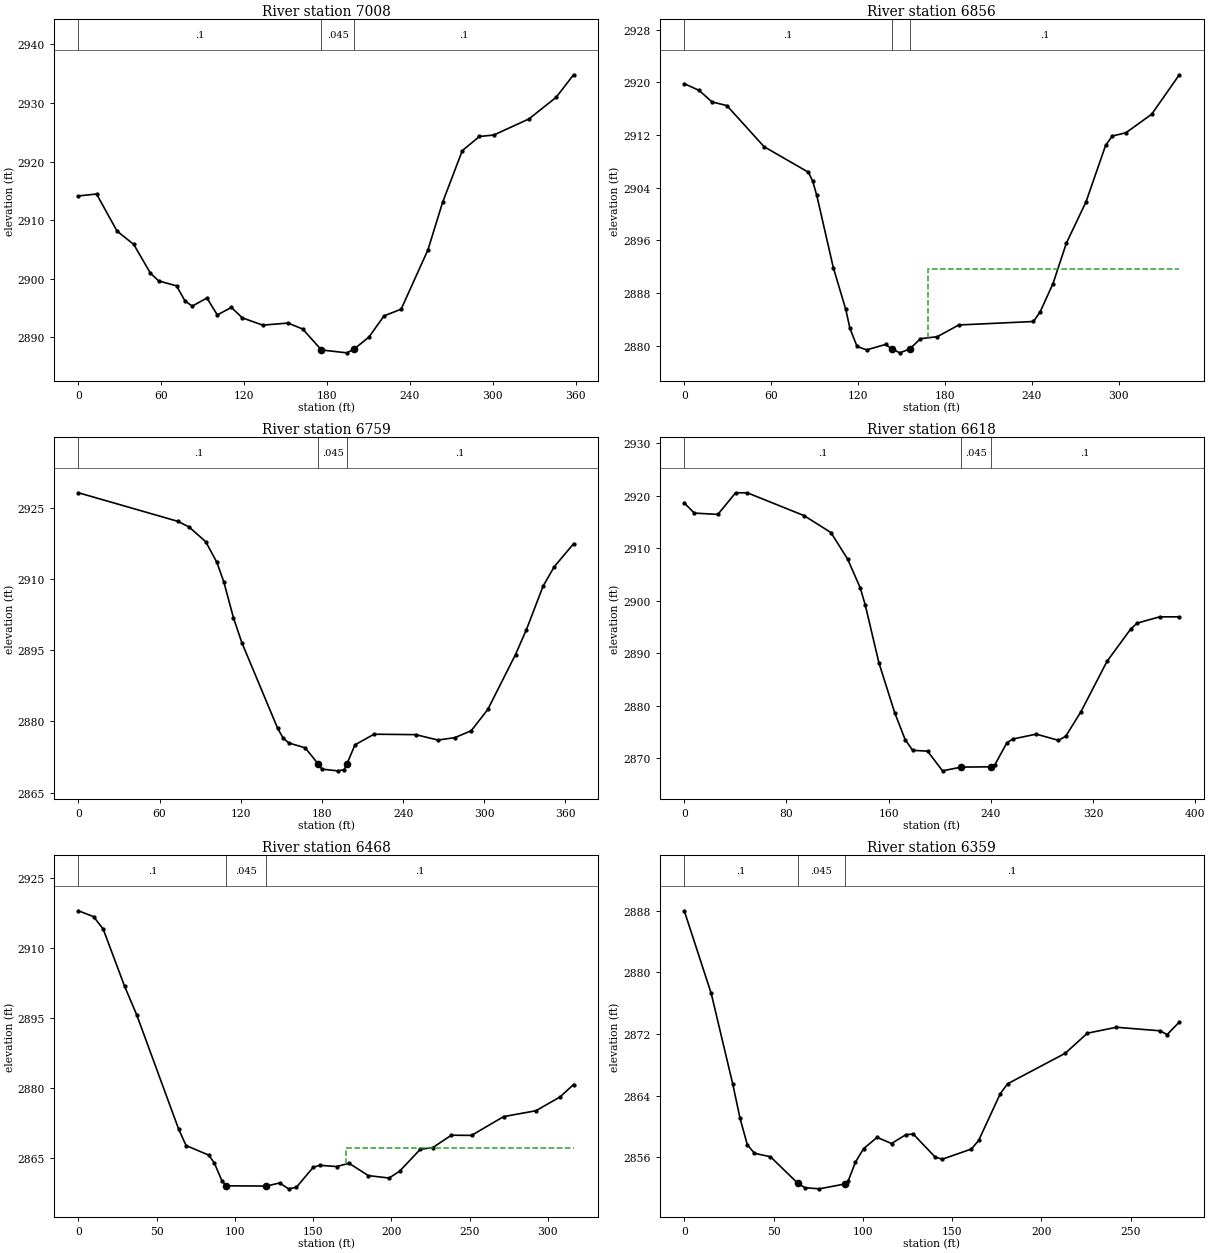
Type RM Length L Ch R = 1 ,7008    ,152.3,152.3,152.3
XS GIS Cut Line= 2
2213053.74948141514494.9729634682213290.72632355514226.050823644
#Sta/Elev= 30
       0 2914.15    13.1 2914.48    27.9 2908.15      40 2905.88    52.1 2900.96
    58.1 2899.65      71  2898.8      77 2896.27    82.3 2895.34      93 2896.73
   100.5 2893.84   110.7 2895.12   118.6 2893.34   133.4  2892.1   151.7 2892.45
   162.3 2891.44   175.9 2887.86   194.3 2887.37199.17242887.949   210.3 2890.06
   221.2 2893.68   233.6 2894.82     253 2904.95   263.6 2913.05   277.9 2921.89
   290.3  2924.3   300.6 2924.54   326.1 2927.29   345.9    2931   358.4 2934.83
#Mann= 3 ,-1,0
       0      .1       0   175.9    .045       0199.1724      .1       0
Bank Sta=175.9,199.1724
XS Rating Curve= 0 ,0
Exp/Cntr=0.3,0.1

Type RM Length L Ch R = 1 ,6856    ,103.4,96.5,93.4
XS GIS Cut Line= 4
2213171.46844484514562.906976419 2213243.1864044514516.893108957
2213293.18191439514446.9893863742213373.16505152514296.296519315
#Sta/Elev= 30
       0 2919.79    10.3 2918.76    19.1 2917.02    29.4 2916.46    55.1 2910.22
    85.7 2906.34    88.6 2905.02    91.4  2902.9   102.9 2891.86   111.5 2885.51
   114.4 2882.61   119.3 2879.88   125.9 2879.36     139 2880.19   143.1 2879.53
   148.8 2878.91   155.7  2879.5   163.1 2881.06   174.7 2881.36   189.5 2883.14
   241.1 2883.67   245.7 2885.13   254.6 2889.43   263.8 2895.56   277.4 2901.85
   290.9 2910.41   295.5 2911.84   304.9 2912.33   322.7 2915.14   341.8 2921.14
#Mann= 3 ,-1,0
       0      .1       0   143.1    .045       0   155.7      .1       0
#XS Ineff= 2 , 0
                          168.28         2891.62
Permanent Ineff=
       F       F
Bank Sta=143.1,155.7
XS Rating Curve= 0 ,0
Exp/Cntr(USF)=0,0
Exp/Cntr=0.3,0.1

Type RM Length L Ch R = 1 ,6759    ,135.9,140.8,146.4
XS GIS Cut Line= 2
2213332.85975427514681.2318303352213409.12925964514323.169250677
#Sta/Elev= 30
       0 2928.15    73.7 2922.12    81.8 2920.94    94.1 2917.85   102.3 2913.53
   107.4 2909.47   114.6 2901.85   120.8  2896.6   147.3 2878.56   151.4 2876.48
   155.5 2875.48   167.7 2874.45  177.44    2871     180 2869.97   191.6 2869.61
   196.4 2869.83   198.4 2870.96   198.4 2870.99   204.5 2875.09   218.6 2877.32
   249.5 2877.23   265.8 2876.09   278.2 2876.59   290.4 2878.04   302.7 2882.53
   323.2  2894.1   331.3 2899.36   343.6  2908.5   351.8 2912.56   366.1 2917.41
#Mann= 3 ,-1,0
       0      .1       0  177.44    .045       0   198.4      .1       0
Bank Sta=177.44,198.4
XS Rating Curve= 0 ,0
Exp/Cntr(USF)=0,0
Exp/Cntr=0.3,0.1

Type RM Length L Ch R = 1 ,6618    ,147.7,150.7,157.1
XS GIS Cut Line= 2
2213394.88073732514728.0052201352213588.25077455514392.132156304
#Sta/Elev= 30
       0 2918.65     7.9 2916.73    26.3 2916.48    40.2  2920.6    49.4 2920.59
    93.8 2916.25   114.8 2913.03   127.9 2907.97   137.8 2902.48   141.7 2899.22
   152.4 2888.21   164.8 2878.67   172.9  2873.6   178.8 2871.54   190.5 2871.38
   202.2 2867.63   216.8 2868.34   240.3  2868.4   243.3 2868.83   252.5 2872.94
   257.1 2873.69   275.6 2874.62     293 2873.44   298.7 2874.23   310.6  2878.9
     331 2888.49   349.4  2894.6   354.5 2895.76   372.1 2896.96   387.6 2896.97
#Mann= 3 ,-1,0
       0      .1       0   216.8    .045       0   240.3      .1       0
Bank Sta=216.8,240.3
XS Rating Curve= 0 ,0
Exp/Cntr=0.3,0.1

Type RM Length L Ch R = 1 ,6468    ,128.5,108.9,93.9
XS GIS Cut Line= 3
2213484.44593796514739.1017132872213607.31858341514628.980002745
2213643.25303632514481.764663387
#Sta/Elev= 30
       0 2917.91     9.7 2916.64    15.8 2913.99    29.5 2901.75    37.2 2895.67
    64.1 2871.15    68.8 2867.69    83.3 2865.64    86.8 2863.99    91.8 2860.09
    94.6 2859.08   120.1 2859.02   128.6 2859.69   134.3 2858.43   139.3 2858.76
     150 2863.01   154.1 2863.47     165  2863.2     173  2863.9   185.3 2861.26
   198.6 2860.74   205.3  2862.2   218.5 2866.88   226.6 2867.27   238.4  2869.9
   251.3 2869.86   271.8 2873.88   292.4 2875.13   307.9 2878.09   316.5 2880.74
#Mann= 3 ,-1,0
       0      .1       0    94.6    .045       0   120.1      .1       0
#XS Ineff= 2 , 0
                          170.96         2867.12
Permanent Ineff=
       F       F
Bank Sta=94.6,120.1
XS Rating Curve= 0 ,0
Exp/Cntr(USF)=0,0
Exp/Cntr=0.3,0.1

Type RM Length L Ch R = 1 ,6359    ,173.6,160.2,151.2
XS GIS Cut Line= 3
2213679.18748924514768.0811107992213660.64067483 514641.73093765
2213687.30172054514494.515598292
#Sta/Elev= 30
       0 2888.02    15.1 2877.27    27.2 2865.46    31.2 2861.08    35.3 2857.62
    39.3  2856.5    48.3 2856.05    63.6  2852.6    67.6 2852.03    75.7 2851.88
    89.9 2852.51    91.9 2852.95    95.9 2855.36   100.4 2857.09     108 2858.57
   116.1 2857.77   124.2 2858.93   128.3 2858.99   140.5 2856.02   144.5 2855.73
   160.8 2857.05   164.9 2858.17     177 2864.24   181.1 2865.53   213.4  2869.5
   225.8 2872.11   242.1 2872.88   266.5 2872.42   270.5 2871.93   277.3 2873.56
#Mann= 3 ,-1,0
       0      .1       0    63.6    .045       0    89.9      .1       0
Bank Sta=63.6,89.9
XS Rating Curve= 0 ,0
Exp/Cntr(USF)=0,0
Exp/Cntr=0.3,0.1

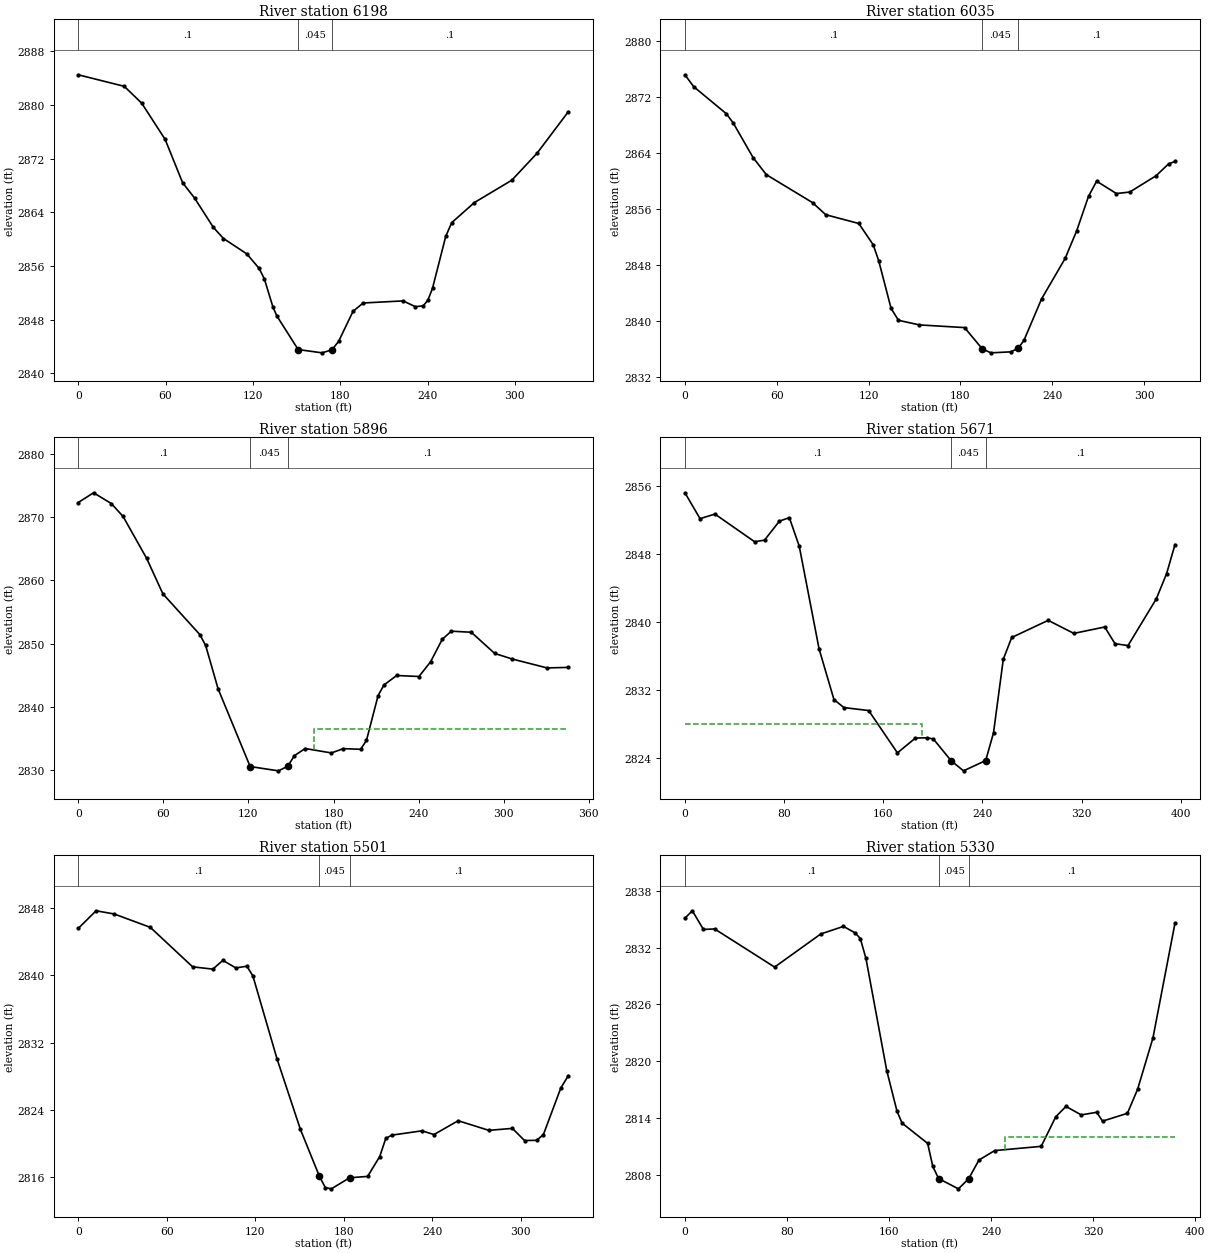
Type RM Length L Ch R = 1 ,6198    ,140.5,163.6,180.3
XS GIS Cut Line= 4
2213850.21954777514780.676354034 2213840.3129394514653.322696654
2213788.15002388514603.478132935 2213748.3620331514472.564816572
#Sta/Elev= 30
       0 2884.51    31.6 2882.79    43.6 2880.28    59.7 2874.88    71.7 2868.43
    79.9 2866.14    92.9 2861.75    99.8 2860.11   115.8 2857.82   124.3 2855.65
   127.9 2854.07   133.7 2849.95   136.4 2848.59   151.1 2843.56   167.5 2843.07
   174.3 2843.52   178.9 2844.78   188.8 2849.26   195.8  2850.5   223.2 2850.81
   231.6 2849.95     237 2850.07   240.2  2850.9   243.4 2852.69   252.5 2860.43
   256.6 2862.47   272.2 2865.47   297.9  2868.8   315.2 2872.81   336.7    2879
#Mann= 3 ,-1,0
       0      .1       0   151.1    .045       0   174.3      .1       0
Bank Sta=151.1,174.3
XS Rating Curve= 0 ,0
Exp/Cntr(USF)=0,0
Exp/Cntr=0.3,0.1

Type RM Length L Ch R = 1 ,6035    ,130.5,138.5,145.6
XS GIS Cut Line= 2
2213881.99892167514786.4879333142214002.22528741514489.753798834
#Sta/Elev= 30
       0 2875.14     5.7 2873.45    27.1 2869.58    31.6 2868.25    44.6 2863.31
    53.2  2860.9    83.4 2856.91      92 2855.19   113.6 2853.94     123 2850.91
   126.6 2848.63   134.7 2841.83   139.5 2840.14   153.2 2839.48   182.7  2839.1
   194.3 2836.06   199.9  2835.5   212.9 2835.64   217.7 2836.14   221.5 2837.27
     233 2843.18   248.4 2848.95     256 2852.92   263.7 2857.82     269 2859.97
   281.9 2858.21   290.6 2858.42   307.8 2860.74     316 2862.44   320.2 2862.78
#Mann= 3 ,-1,0
       0      .1       0   194.3    .045       0   217.7      .1       0
Bank Sta=194.3,217.7
XS Rating Curve= 0 ,0
Exp/Cntr=0.3,0.1

Type RM Length L Ch R = 1 ,5896    ,242.9,225.2,189.1
XS GIS Cut Line= 4
2213980.96533315514827.5994787692214007.28806166514733.753229299
2214069.08925033514681.1077722792214106.85664341 514518.59353539
#Sta/Elev= 30
       0 2872.33    10.8 2873.87    23.3 2872.17    31.6 2870.13    48.2 2863.51
    59.7 2857.88    85.7 2851.45    89.8 2849.74    98.6 2842.86   121.2 2830.57
   141.1 2829.89   147.7 2830.61   152.4 2832.29     160 2833.42   178.5 2832.72
   186.8  2833.4   199.1  2833.3   203.2  2834.7   211.4 2841.79   215.5 2843.46
   224.5 2844.97   240.2 2844.81   248.4 2847.13   256.6 2850.68     263 2851.98
   277.1 2851.81   293.6 2848.46   305.9 2847.58   330.5 2846.17   345.5 2846.25
#Mann= 3 ,-1,0
       0      .1       0   121.2    .045       0   147.7      .1       0
#XS Ineff= 2 , 0
                          166.42         2836.44
Permanent Ineff=
       F       F
Bank Sta=121.2,147.7
XS Rating Curve= 0 ,0
Exp/Cntr(USF)=0,0
Exp/Cntr=0.3,0.1

Type RM Length L Ch R = 1 ,5671    ,148.4,170.4,179.7
XS GIS Cut Line= 4
2214254.49281636514897.4119326442214254.49281636514744.053427411
2214190.40269477514650.2071779412214156.06870106514526.604800589
#Sta/Elev= 30
       0 2855.18    12.2 2852.14    24.2 2852.68    56.2 2849.43    64.2 2849.62
    76.2 2851.85    84.2 2852.26    92.2 2848.91   108.2 2836.85   120.2  2830.9
   128.2 2829.96   148.2 2829.61   171.4 2824.64   185.9 2826.38   195.6 2826.41
   200.4 2826.27   214.7 2823.72   224.7 2822.53   242.6 2823.74   248.9 2826.99
   256.8 2835.64   263.6 2838.19     293  2840.2   313.7 2838.67   338.6 2839.42
   346.9 2837.46   357.4 2837.24   380.2 2842.72   388.5 2845.68   395.3  2849.1
#Mann= 3 ,-1,0
       0      .1       0   214.7    .045       0   242.6      .1       0
#XS Ineff= 2 , 0
          191.55 2828.08
Permanent Ineff=
       F       F
Bank Sta=214.7,242.6
XS Rating Curve= 0 ,0
Exp/Cntr(USF)=0,0
Exp/Cntr=0.3,0.1

Type RM Length L Ch R = 1 ,5501    ,172.4,170.6,168.3
XS GIS Cut Line= 2
2214328.80391176514897.0073803252214399.30823466514572.193069448
#Sta/Elev= 30
       0 2845.58    12.1 2847.68    24.4  2847.3    48.9 2845.71    77.6 2841.02
    91.3 2840.75    98.1 2841.79   106.9 2840.89   114.4  2841.1   118.5 2839.92
   134.9 2830.05   150.7 2821.71   163.6 2816.13   167.6  2814.8   171.7 2814.65
     184 2815.96   196.3 2816.13   204.5 2818.49   208.6 2820.64   212.7 2821.03
   233.1 2821.54   241.3  2821.1   257.7 2822.74   278.5  2821.6   294.5 2821.83
   302.7 2820.39   310.9 2820.41   315.5 2821.09   327.3 2826.62   332.4 2828.09
#Mann= 3 ,-1,0
       0      .1       0   163.6    .045       0     184      .1       0
Bank Sta=163.6,184
XS Rating Curve= 0 ,0
Exp/Cntr=0.3,0.1

Type RM Length L Ch R = 1 ,5330    ,234,249.2,263.6
XS GIS Cut Line= 3
2214468.40920936514950.4160867132214528.16452387514818.649679322
2214548.35100147514579.972515349
#Sta/Elev= 30
       0  2835.1     5.8 2835.88    14.5 2833.91    23.3 2833.96    70.3 2829.93
   106.5 2833.43   124.3 2834.23   133.7 2833.52   137.5 2832.94   141.9 2830.85
   158.2    2819   166.2 2814.73   170.2 2813.45   190.3  2811.3   194.3 2808.87
   198.9 2807.58   214.4  2806.5   222.4 2807.56   230.5 2809.54   242.8 2810.54
   279.3 2810.99   290.7 2814.11   298.7 2815.21   310.7 2814.31   322.8 2814.59
   327.4 2813.65   346.9 2814.48   354.9 2817.03   366.9 2822.44   384.2 2834.58
#Mann= 3 ,-1,0
       0      .1       0   198.9    .045       0   222.4      .1       0
#XS Ineff= 2 , 0
                          251.04         2812.03
Permanent Ineff=
       F       F
Bank Sta=198.9,222.4
XS Rating Curve= 0 ,0
Exp/Cntr=0.3,0.1

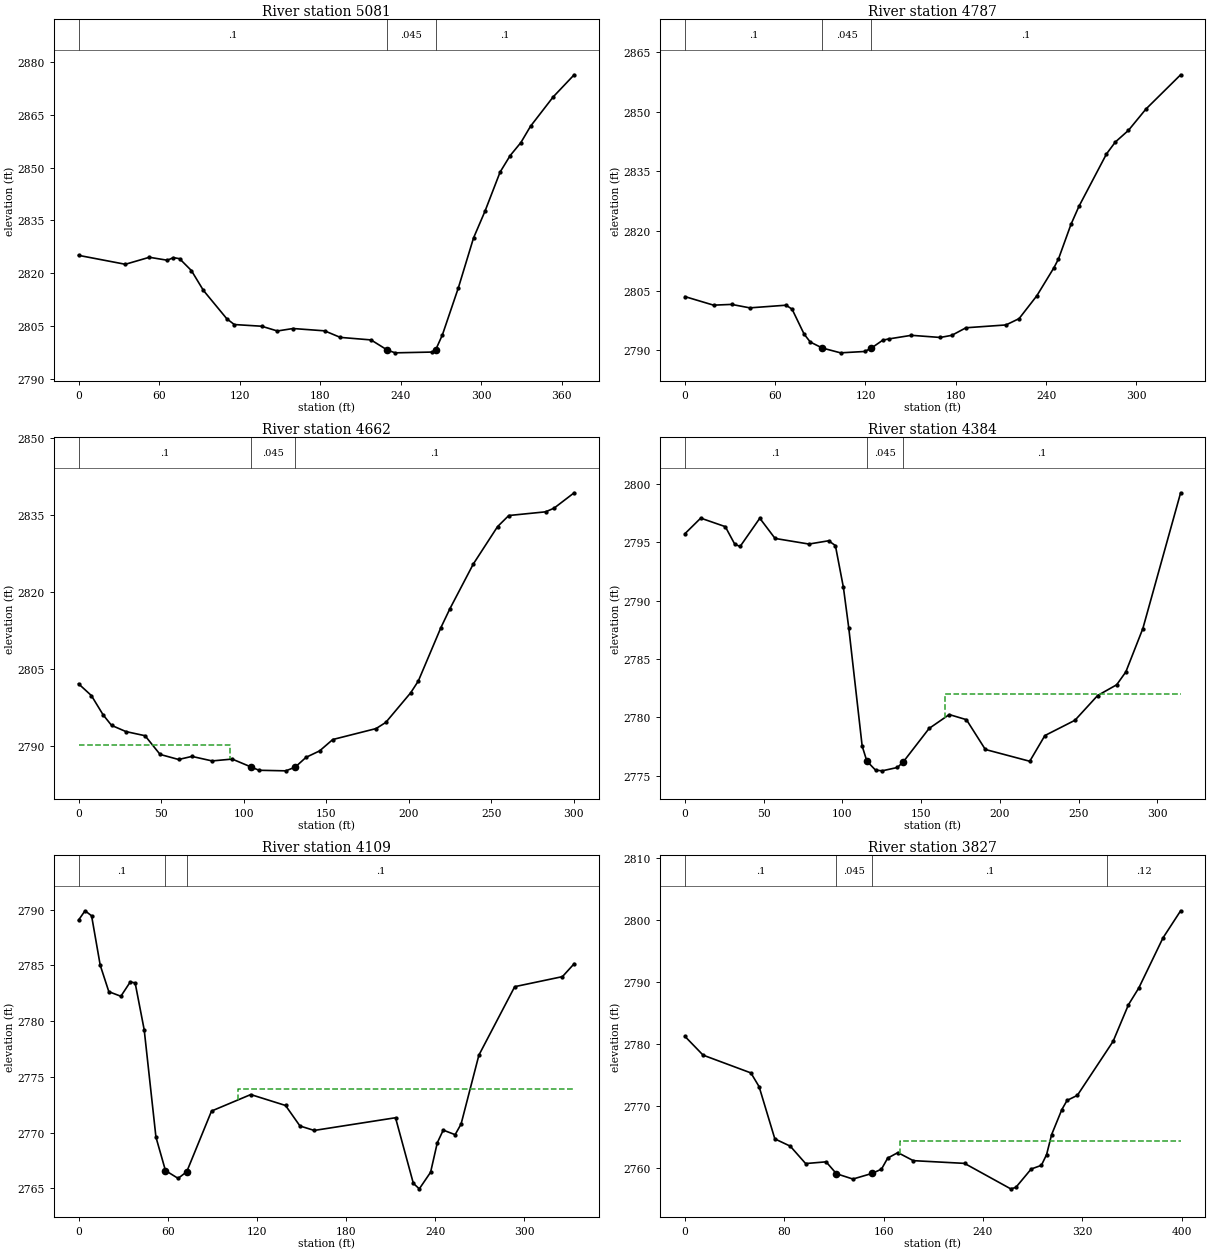
Type RM Length L Ch R = 1 ,5081    ,301.9,294.2,277.4
XS GIS Cut Line= 3
2214626.44441487 515000.413913772214671.07860669514911.145530127
2214855.33770626 514714.29729953
#Sta/Elev= 30
       0 2825.05    34.9 2822.51    52.8  2824.5    66.2 2823.66    70.7  2824.4
    75.3  2824.1    84.1 2820.74    93.1 2815.08   110.5 2807.04   116.1 2805.39
   136.5 2804.91   148.2 2803.56   159.9 2804.26   183.4  2803.6   195.1 2801.74
     218 2801.02   230.2 2798.13     236 2797.35   263.3 2797.57   266.1 2798.13
   271.2 2802.46   283.1 2815.83   294.4 2829.99   302.9 2837.55   314.2 2848.71
   321.7 2853.39   329.7  2857.1   336.9 2861.74   353.8 2870.08   369.4 2876.35
#Mann= 3 ,-1,0
       0      .1       0   230.2    .045       0   266.1      .1       0
Bank Sta=230.2,266.1
XS Rating Curve= 0 ,0
Exp/Cntr(USF)=0,0
Exp/Cntr=0.3,0.1

Type RM Length L Ch R = 1 ,4787    ,123.8,125.3,127
XS GIS Cut Line= 3
2214864.49343792515148.0500867182214880.51596832514983.246916916
2214966.35095259514843.622009167
#Sta/Elev= 30
       0  2803.5      19 2801.35      31 2801.54    43.1 2800.67    67.2 2801.34
    71.2 2800.34    79.2 2794.06    83.3 2792.07    91.3 2790.56   103.4 2789.35
   119.4 2789.69   123.7 2790.49   131.5 2792.54   135.5 2792.85   150.5 2793.76
   169.7 2793.22   177.4 2793.76   186.8 2795.66   213.4 2796.37   222.1 2797.96
   233.9 2803.71   245.3 2810.79   248.3 2812.98   256.6 2821.68   261.9 2826.22
   280.2  2839.4   286.1 2842.41   294.8 2845.34   306.4 2850.69   329.5 2859.33
#Mann= 3 ,-1,0
       0      .1       0    91.3    .045       0   123.7      .1       0
Bank Sta=91.3,123.7
XS Rating Curve= 0 ,0
Exp/Cntr(USF)=0,0
Exp/Cntr=0.3,0.1

Type RM Length L Ch R = 1 ,4662    ,251.6,277.6,290.7
XS GIS Cut Line= 3
2214978.54988201 515172.836612812215009.84067795514996.980514399
2215068.50299041514890.535443105
#Sta/Elev= 30
       0 2802.12     7.8 2799.82    14.9 2796.07      20 2794.02    28.7 2792.81
    40.3    2792    49.4 2788.36    60.6 2787.37    68.7 2787.97    80.9 2787.09
    93.1 2787.45   104.6  2785.9   109.3 2785.27   125.6 2785.16  131.292785.897
   137.8 2787.79     146 2789.04     154 2791.26   180.2 2793.39   186.1 2794.59
   201.2 2800.37   205.8 2802.65   219.5 2813.07   224.9 2816.71   239.1 2825.44
   253.8 2832.73   260.6 2834.89   282.9 2835.61     288 2836.32   300.2 2839.32
#Mann= 3 ,-1,0
       0      .1       0   104.6    .045       0  131.29      .1       0
#XS Ineff= 2 , 0
           91.89 2790.22
Permanent Ineff=
       F       F
Bank Sta=104.6,131.29
XS Rating Curve= 0 ,0
Exp/Cntr=0.3,0.1

Type RM Length L Ch R = 1 ,4384    ,283.9,274.8,267.6
XS GIS Cut Line= 3
2215014.41854378515308.2753906932215184.17538736515246.758774951
2215296.20537044515172.918343584
#Sta/Elev= 30
       0 2795.73      10 2797.06    25.6 2796.33    31.6 2794.83      35 2794.63
    47.5 2797.05    57.2 2795.32    78.7 2794.84    91.2 2795.12    95.5 2794.71
   100.6 2791.12     104 2787.65   112.5 2777.54115.48952776.249     121 2775.48
   125.2 2775.42   134.9 2775.71138.68742776.202     155 2779.05   167.8 2780.24
   178.7  2779.8   190.7 2777.25   218.9 2776.24   228.5 2778.44   247.6 2779.75
     262 2781.87   274.1 2782.79   279.9 2783.89   290.7  2787.6   314.7 2799.23
#Mann= 3 ,-1,0
       0      .1       0115.4895    .045       0138.6874      .1       0
#XS Ineff= 2 , 0
                          164.85         2782.01
Permanent Ineff=
       F       F
Bank Sta=115.4895,138.6874
XS Rating Curve= 0 ,0
Exp/Cntr(USF)=0,0
Exp/Cntr=0.3,0.1

Type RM Length L Ch R = 1 ,4109    ,286.2,281.9,279.5
XS GIS Cut Line= 3
2215227.53002996515560.806264023  2215337.737911515396.907364014
2215347.62836186515261.266895041
#Sta/Elev= 30
       0 2789.06     4.4  2789.9     8.8 2789.45    14.6 2785.02    20.4 2782.64
    28.5 2782.23    34.8 2783.51    38.1 2783.43    44.2 2779.22    52.1 2769.59
    58.5 2766.59      67 2765.89    72.8 2766.48    89.5 2771.93   115.9 2773.41
   139.3 2772.43     149 2770.59   158.6 2770.19   213.3 2771.33   225.3 2765.44
   229.3 2764.95   236.9 2766.44   241.4 2769.08   245.4 2770.22   253.4 2769.81
   257.4 2770.76   269.4 2776.95   293.5 2783.09   325.6 2783.99   333.5 2785.15
#Mann= 3 ,-1,0
       0      .1       0    58.5    .045       0    72.8      .1       0
#XS Ineff= 2 , 0
                          107.46         2773.92
Permanent Ineff=
       F       F
Bank Sta=58.5,72.8
XS Rating Curve= 0 ,0
Exp/Cntr(USF)=0,0
Exp/Cntr=0.3,0.1

Type RM Length L Ch R = 1 ,3827    ,302.4,301.3,293
XS GIS Cut Line= 2
2215501.75911388515695.3432082062215600.73522072515308.547048168
#Sta/Elev= 30
       0 2781.16    14.6 2778.14    53.1 2775.27    59.7 2773.06    72.4 2764.62
    84.8 2763.45    97.2 2760.64   113.7 2760.92     122    2759   135.3 2758.14
   150.9 2759.06   158.3 2759.74   163.3 2761.52   171.5 2762.41   183.9 2761.11
   225.2 2760.67   262.4 2756.56   266.5 2756.78   278.9 2759.76   287.1 2760.35
   291.3 2762.08   295.4 2765.33   303.6 2769.35   307.8 2770.83   316.1 2771.65
   344.9 2780.37   357.3 2786.29   365.6 2788.98   385.1 2797.07   399.3 2801.44
#Mann= 4 ,-1,0
       0      .1       0     122    .045       0   150.9      .1       0
     340     .12       0
#XS Ineff= 2 , 0
                          173.07         2764.21
Permanent Ineff=
       F       F
Bank Sta=122,150.9
XS Rating Curve= 0 ,0
Exp/Cntr=0.3,0.1

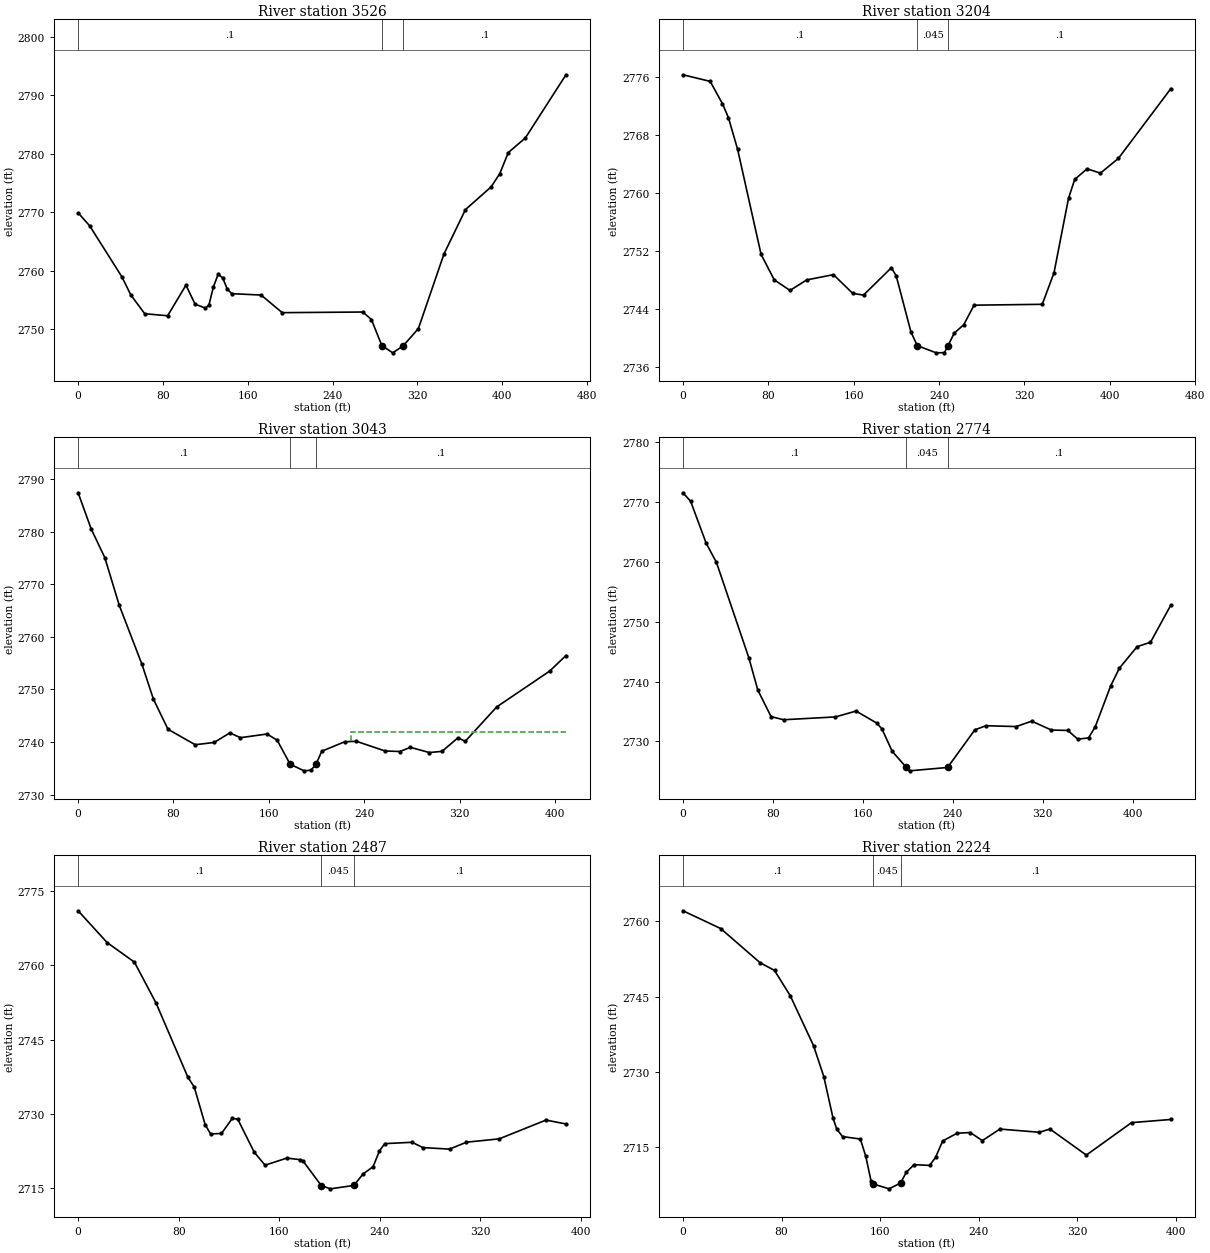
Type RM Length L Ch R = 1 ,3526    ,307.8,322.4,337
XS GIS Cut Line= 3
2215702.63698564  515803.25633382215794.94466743515578.369474535
2215823.16666011515363.194906116
#Sta/Elev= 30
       0 2769.93    10.9 2767.71    41.2 2759.01    49.8 2755.86    62.8 2752.68
    84.4 2752.33   101.7 2757.56   110.3 2754.32   119.9 2753.64   123.3 2754.13
   127.6 2757.27     132 2759.39   136.3 2758.84   140.7 2756.87   144.9 2756.11
   172.6 2755.87   192.5 2752.86   268.5 2752.97   276.6 2751.69  286.412747.242
   296.7 2745.99  306.652747.201   320.9 2750.14   345.1 2762.93   365.3 2770.49
   389.5 2774.37   397.6 2776.61   405.7 2780.24   421.8 2782.74   460.1 2793.54
#Mann= 3 ,-1,0
       0      .1       0  286.41    .045       0  306.65      .1       0
Bank Sta=286.41,306.65
XS Rating Curve= 0 ,0
Exp/Cntr=0.3,0.1

Type RM Length L Ch R = 1 ,3204    ,167,160.5,153.8
XS GIS Cut Line= 3
2215767.47747246515869.0639546032216055.88301962515716.849915827
2216146.29586972515621.859199899
#Sta/Elev= 30
       0 2776.33    25.5 2775.42      37 2772.34    42.6 2770.42    51.2 2766.05
    73.2 2751.57    85.5 2748.07   100.3  2746.6   115.9 2748.05     141 2748.78
   159.1 2746.19   169.2 2745.96   195.3 2749.73   199.8 2748.63   213.6  2740.9
   219.5    2739   237.3    2738     245 2738.03   248.3 2738.95   254.1  2740.7
   263.1 2741.87   272.8 2744.57   336.7 2744.69   347.7 2749.03   361.3  2759.3
   367.1  2761.9   378.7 2763.37   391.2 2762.77   408.1 2764.81   457.2 2774.42
#Mann= 3 ,-1,0
       0      .1       0   219.5    .045       0   248.3      .1       0
Bank Sta=219.5,248.3
XS Rating Curve= 0 ,0
Exp/Cntr(USF)=0,0
Exp/Cntr=0.3,0.1

Type RM Length L Ch R = 1 ,3043    ,258.2,269.3,274.2
XS GIS Cut Line= 2
2215954.59235433516023.1682392492216223.76841698 515714.85115518
#Sta/Elev= 30
       0 2787.43      11 2780.52    22.4 2775.08    34.5 2766.02    53.6 2754.75
    63.2 2748.14    75.4 2742.42    98.2 2739.48   114.1 2739.91   127.3 2741.73
   136.2 2740.82   158.5 2741.52     167 2740.34   177.9 2735.76   189.6 2734.51
   195.3 2734.63  199.542735.729   204.4 2738.24   223.7 2740.05   233.5 2740.13
   257.5 2738.29     270 2738.19   278.8 2738.98   294.7 2737.99   305.3 2738.22
   318.7  2740.8   324.8 2740.13   351.2 2746.68   395.6 2753.49   409.3 2756.46
#Mann= 3 ,-1,0
       0      .1       0   177.9    .045       0  199.54      .1       0
#XS Ineff= 2 , 0
                           229.3         2741.99
Permanent Ineff=
       F       F
Bank Sta=177.9,199.54
XS Rating Curve= 0 ,0
Exp/Cntr=0.3,0.1

Type RM Length L Ch R = 1 ,2774    ,282.4,286.4,288
XS GIS Cut Line= 2
2216090.21701332516162.0473675842216467.89094412515948.032140133
#Sta/Elev= 30
       0 2771.54     6.8 2770.12    20.6 2763.13    29.8 2759.89    58.6 2743.97
    66.6 2738.56    78.4 2734.13    89.6 2733.61   135.6 2734.08     154 2735.06
   172.4 2733.05     177 2732.08   186.2 2728.33   198.7 2725.65   201.6 2725.07
  235.452725.635   259.7 2731.92   269.5 2732.61   296.5 2732.47   310.3 2733.37
   327.8 2731.89   342.4 2731.82   351.3 2730.37   360.9 2730.57   366.9 2732.47
   380.6 2739.28   388.4 2742.25   404.1 2745.82     416 2746.56   434.1 2752.77
#Mann= 3 ,-1,0
       0      .1       0   198.7    .045       0  235.45      .1       0
Bank Sta=198.7,235.45
XS Rating Curve= 0 ,0
Exp/Cntr(USF)=0,0
Exp/Cntr=0.3,0.1

Type RM Length L Ch R = 1 ,2487    ,277.2,262.9,258.9
XS GIS Cut Line= 2
2216202.82762426516394.7829435092216561.34061584516245.518779697
#Sta/Elev= 30
       0 2771.05    23.1 2764.62    44.8 2760.67    62.1 2752.36    87.4 2737.38
    92.4 2735.44   101.1 2727.83   105.4 2725.94   114.1 2726.03   122.8 2729.12
   127.1  2728.9   140.1 2722.27   148.8 2719.62   166.1 2721.06   176.6 2720.74
   179.1 2720.44  193.512715.508   200.8 2714.84   219.5 2715.53   226.8 2717.85
   234.8 2719.32   239.8  2722.5   244.1 2723.98   265.8 2724.25   274.4 2723.18
   295.6 2722.87   309.1 2724.27   335.1 2724.94   372.4 2728.74   388.3 2727.95
#Mann= 3 ,-1,0
       0      .1       0  193.51    .045       0   219.5      .1       0
Bank Sta=193.51,219.5
XS Rating Curve= 0 ,0
Exp/Cntr(USF)=0,0
Exp/Cntr=0.3,0.1

Type RM Length L Ch R = 1 ,2224    ,425.2,422.4,418.8
XS GIS Cut Line= 2
2216379.79440874516695.1330697042216589.04323651516358.939953081
#Sta/Elev= 30
       0  2762.1    30.6 2758.56    62.7 2751.72    74.3 2750.21    87.1 2745.15
     106  2735.2   114.3 2729.05   121.8 2720.76   124.8 2718.59   129.5 2717.08
     144 2716.59   148.4 2713.11   152.7 2708.17   154.6 2707.61   167.3 2706.66
   176.6 2707.82   181.3 2709.97   187.6 2711.48   200.2 2711.33     205 2712.92
   210.8  2716.2   222.4 2717.74   233.2 2717.89     243 2716.27   257.2 2718.58
   289.2 2717.94   297.9 2718.58   327.4 2713.39   364.1 2719.86     396 2720.49
#Mann= 3 ,-1,0
       0      .1       0   154.6    .045       0   176.6      .1       0
Bank Sta=154.6,176.6
XS Rating Curve= 0 ,0
Exp/Cntr(USF)=0,0
Exp/Cntr=0.3,0.1

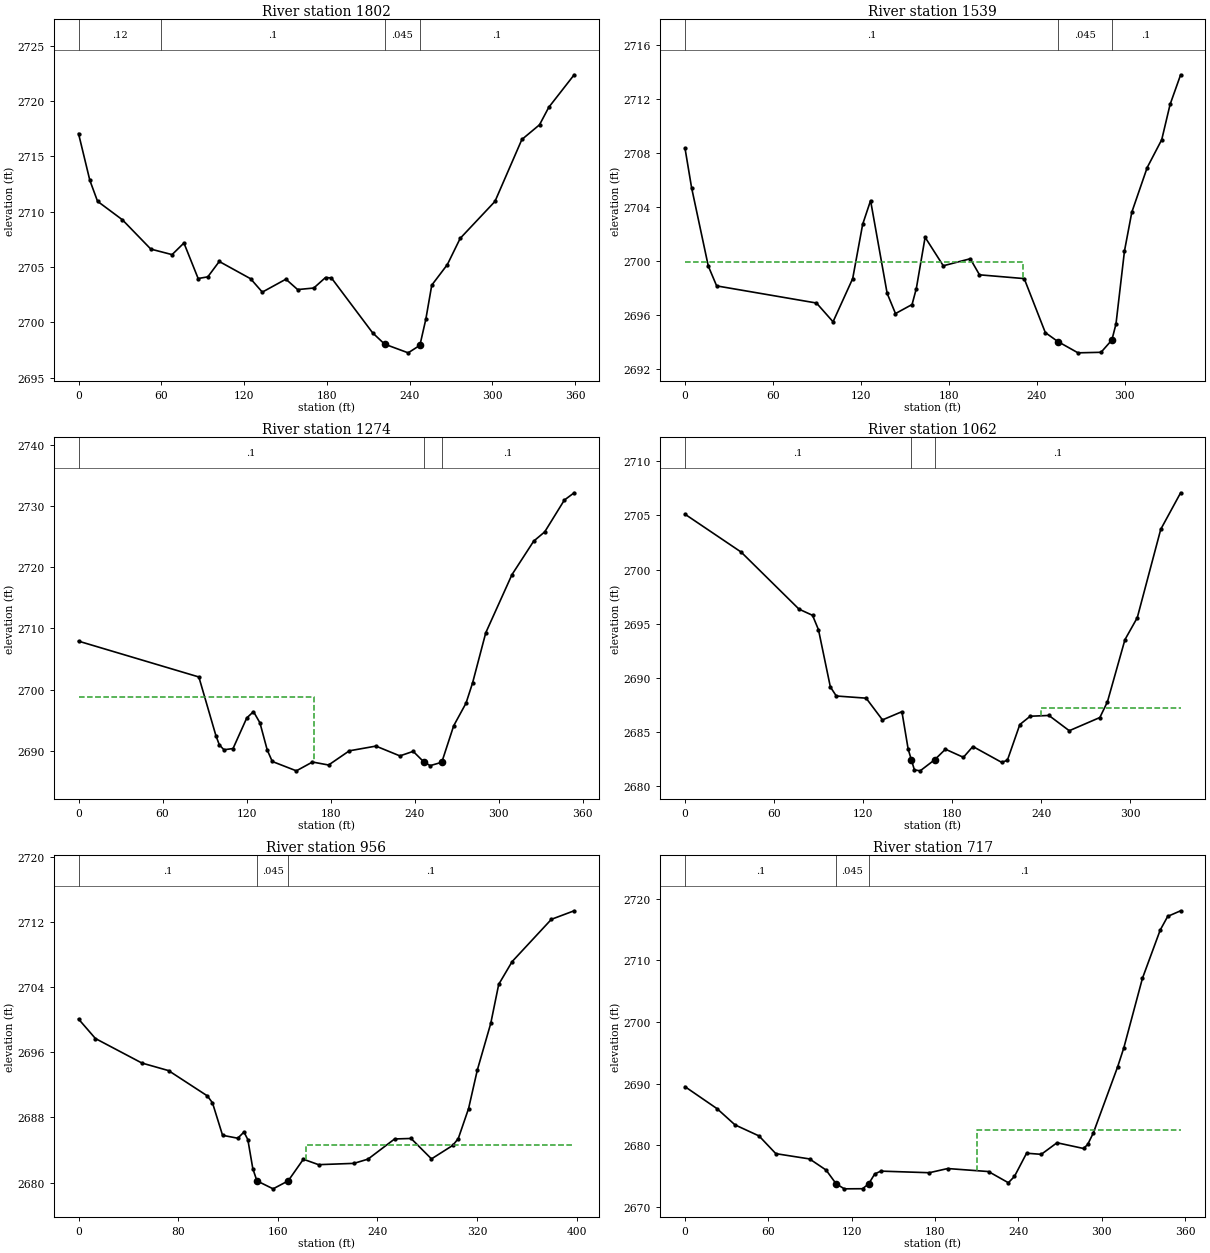
Type RM Length L Ch R = 1 ,1802    ,255,263.3,275.1
XS GIS Cut Line= 4
2216695.58259421516876.0552473872216819.89261884516774.505877022
2216860.86734384516665.7109175332216908.05171116516598.129073942
#Sta/Elev= 30
       0 2717.07     8.2 2712.84    13.8 2710.94    31.8 2709.27    52.4 2706.62
    67.8 2706.12    76.4 2707.17    86.7 2703.96    93.7 2704.11     102  2705.5
   124.7 2703.94   133.2 2702.73   150.3  2703.9   158.8 2702.96   170.5  2703.1
     179 2704.05   183.3 2704.01   213.2 2699.04   221.8 2698.03   238.9 2697.24
   247.4 2697.92   251.7 2700.28     256 2703.36   267.3 2705.22   276.6 2707.59
   301.8 2710.93   321.3 2716.53   334.1 2717.86   340.8 2719.44   359.2 2722.38
#Mann= 4 ,-1,0
       0     .12       0      60      .1       0   221.8    .045       0
   247.4      .1       0
Bank Sta=221.8,247.4
XS Rating Curve= 0 ,0
Exp/Cntr(USF)=0,0
Exp/Cntr=0.3,0.1

Type RM Length L Ch R = 1 ,1539    ,260.3,264.4,270.7
XS GIS Cut Line= 2
2216843.79242381517043.1853691062217101.52532009516824.404677804
#Sta/Elev= 30
       0 2708.39     4.5 2705.46    15.9 2699.65    21.6 2698.18    89.7 2696.91
     101 2695.52   114.4 2698.72   121.2 2702.74   126.6  2704.5   137.9 2697.63
   143.6 2696.13   154.9  2696.8   157.8 2697.98   163.8 2701.78   176.2 2699.67
   194.6 2700.19   200.9    2699   231.4 2698.72   245.8 2694.72   254.3 2694.06
   268.1 2693.22   283.8 2693.26   291.2 2694.17     294 2695.36   299.8 2700.77
   304.8 2703.64   315.3 2706.95   325.2 2709.01   330.9 2711.62   338.1 2713.82
#Mann= 3 ,-1,0
       0      .1       0   254.3    .045       0   291.2      .1       0
#XS Ineff= 2 , 0
          230.51 2699.96
Permanent Ineff=
       F       F
Bank Sta=254.3,291.2
XS Rating Curve= 0 ,0
Exp/Cntr(USF)=0,0
Exp/Cntr=0.3,0.1

Type RM Length L Ch R = 1 ,1274    ,206.1,211.9,220.7
XS GIS Cut Line= 4
2216989.88042293517219.5142218572217160.51512123517099.860690202
2217221.89054877517076.9072782762217290.14020456517035.402136358
#Sta/Elev= 30
       0 2707.93    85.9 2702.08    98.1 2692.48   100.5    2691   103.8 2690.19
   110.3 2690.39   120.1 2695.39   124.9 2696.42   129.5 2694.59   134.7 2690.16
   138.3 2688.28   155.5 2686.75     167 2688.19   178.5  2687.7   193.3 2690.02
   212.3 2690.79   229.4 2689.19   238.9 2689.93   246.5  2688.2     251  2687.6
   259.3 2688.15   267.8 2694.11   276.6  2697.8   281.3 2701.12   290.7  2709.3
   309.4 2718.79   324.9 2724.26   332.8 2725.78   346.8 2730.97   353.8 2732.16
#Mann= 3 ,-1,0
       0      .1       0   246.5    .045       0   259.3      .1       0
#XS Ineff= 2 , 0
          168.36 2698.75
Permanent Ineff=
       F       F
Bank Sta=246.5,259.3
XS Rating Curve= 0 ,0
Exp/Cntr(USF)=0,0
Exp/Cntr=0.3,0.1

Type RM Length L Ch R = 1 ,1062    ,112.6,106.7,97
XS GIS Cut Line= 4
2217010.51490634 517270.567232662217153.79034341517280.959915944
 2217243.0008769517307.6662539942217318.57413138517246.866718433
#Sta/Elev= 30
       0 2705.12    37.8 2701.62    76.8 2696.34    85.9 2695.77    89.9 2694.44
    97.9 2689.15   101.9 2688.31     122 2688.11     133  2686.1   146.1 2686.86
   150.3  2683.4   152.52682.394   154.5 2681.48   158.4 2681.39   168.2 2682.42
   175.4 2683.39   187.5 2682.64   193.9 2683.64   213.2 2682.18   217.1 2682.36
   225.5 2685.67   232.5 2686.44   245.1 2686.51   258.8  2685.1   279.4 2686.32
   284.5 2687.77   296.3 2693.52   304.6 2695.55   320.4 2703.72   333.8  2707.1
#Mann= 3 ,0,0
       0      .1       0   152.5    .045       0   168.2      .1       0
#XS Ineff= 2 , 0
                          240.02         2687.21
Permanent Ineff=
       F       F
Bank Sta=152.5,168.2
XS Rating Curve= 0 ,0
Exp/Cntr(USF)=0,0
Exp/Cntr=0.3,0.1

Type RM Length L Ch R = 1 ,956     ,242.3,239.1,233.2
XS GIS Cut Line= 4
2217025.46063807517447.9806155222217108.12861541 517400.43012447
2217208.44604559517383.4750658482217356.91296776517248.030569512
#Sta/Elev= 30
       0  2700.1    13.6  2697.7    50.9 2694.69    72.3 2693.76   103.5 2690.65
   107.6  2689.8   115.7 2685.81   127.9 2685.45   132.9 2686.21     136 2685.28
     140 2681.71   143.3 2680.21   156.3 2679.23   168.4 2680.21   180.6 2682.87
   192.8  2682.2   221.2 2682.36   232.5 2682.88   253.9 2685.36   267.1 2685.42
   283.5 2682.91   300.5 2684.56     305  2685.4   313.3  2689.1   320.3 2693.82
   331.1 2699.56   337.5 2704.36   348.3 2707.16   379.8 2712.35   398.1  2713.4
#Mann= 3 ,-1,0
       0      .1       0   143.3    .045       0   168.4      .1       0
#XS Ineff= 2 , 0
                          182.99         2684.65
Permanent Ineff=
       F       F
Bank Sta=143.3,168.4
XS Rating Curve= 0 ,0
Exp/Cntr(USF)=0,0
Exp/Cntr=0.3,0.1

Type RM Length L Ch R = 1 ,717     ,176.9,173.8,170.4
XS GIS Cut Line= 2
2217163.23255593517650.517239139 2217489.6174344517506.399240855
#Sta/Elev= 30
       0 2689.49    23.1 2685.91      36 2683.28    53.3 2681.48    65.4  2678.6
    89.7 2677.74   101.6 2675.93   108.8  2673.7   114.7 2672.88   127.8  2672.9
   132.2 2673.68   136.6  2675.3     141 2675.76   175.9  2675.5   189.1 2676.18
   218.5 2675.69   232.8 2673.87   237.2 2674.91   245.9 2678.67   256.5 2678.49
   267.8 2680.37   286.9 2679.44   289.9 2680.09     294 2681.99   311.5 2692.74
   315.9  2695.8   329.3  2707.1   342.1 2714.95   347.5 2717.17   356.8 2718.08
#Mann= 3 ,-1,0
       0      .1       0   108.8    .045       0   132.2      .1       0
#XS Ineff= 2 , 0
                          210.14         2682.41
Permanent Ineff=
       F       F
Bank Sta=108.8,132.2
XS Rating Curve= 0 ,0
Exp/Cntr(USF)=0,0
Exp/Cntr=0.3,0.1