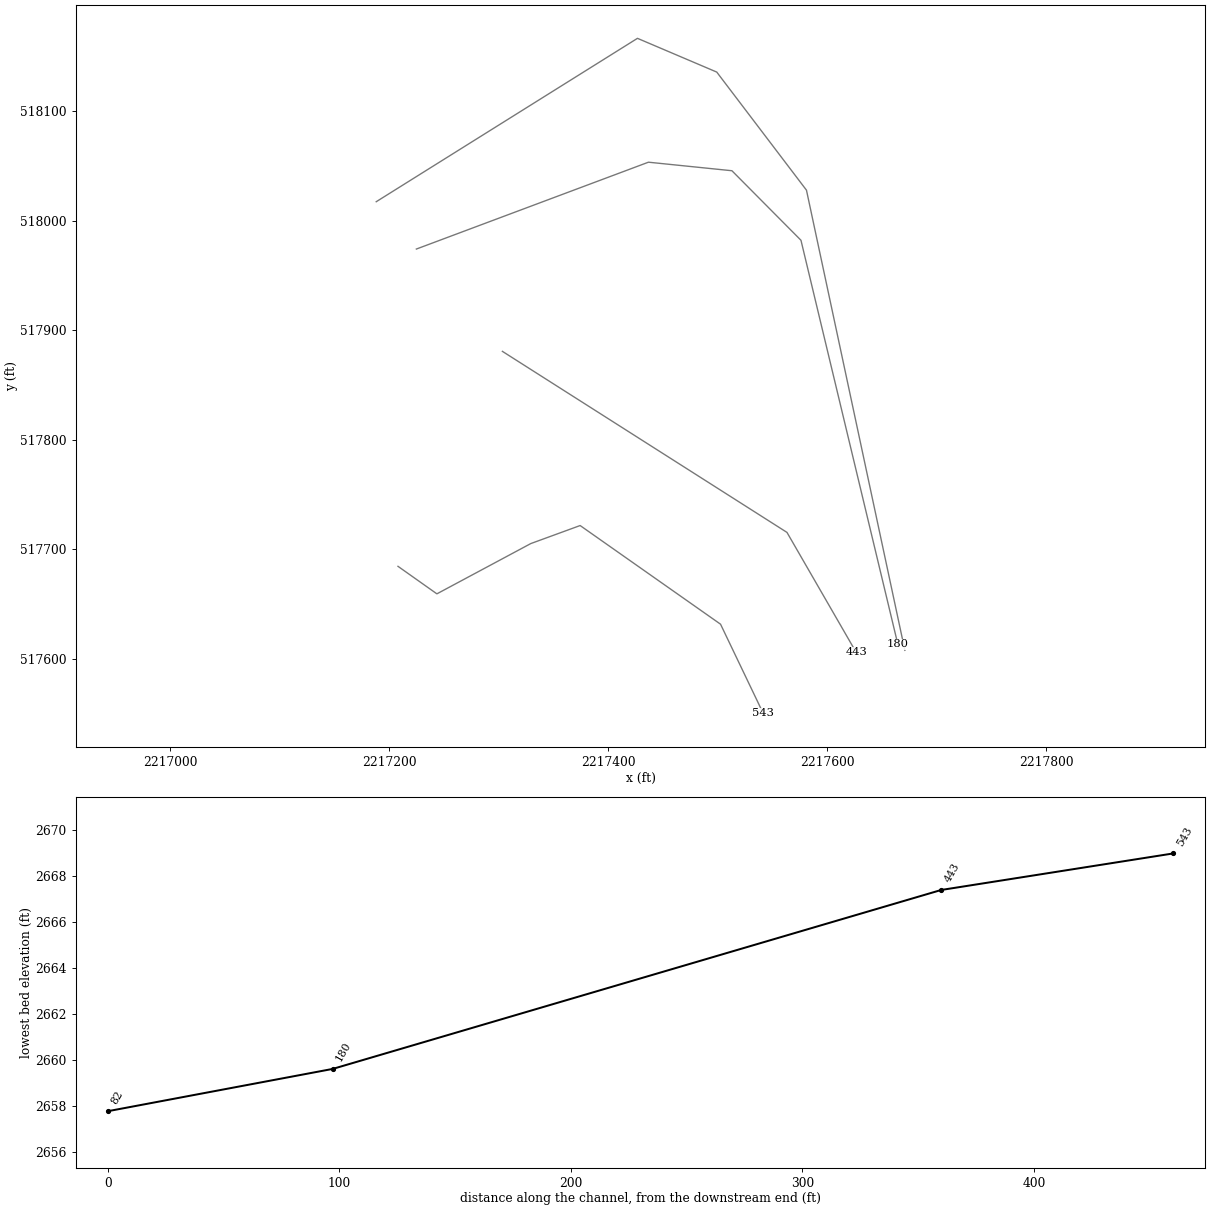
HEC-RAS study LAURELRN4.prj: LAURELRN4

--- LAURELRN4.g01 (geometry) --- (continued)

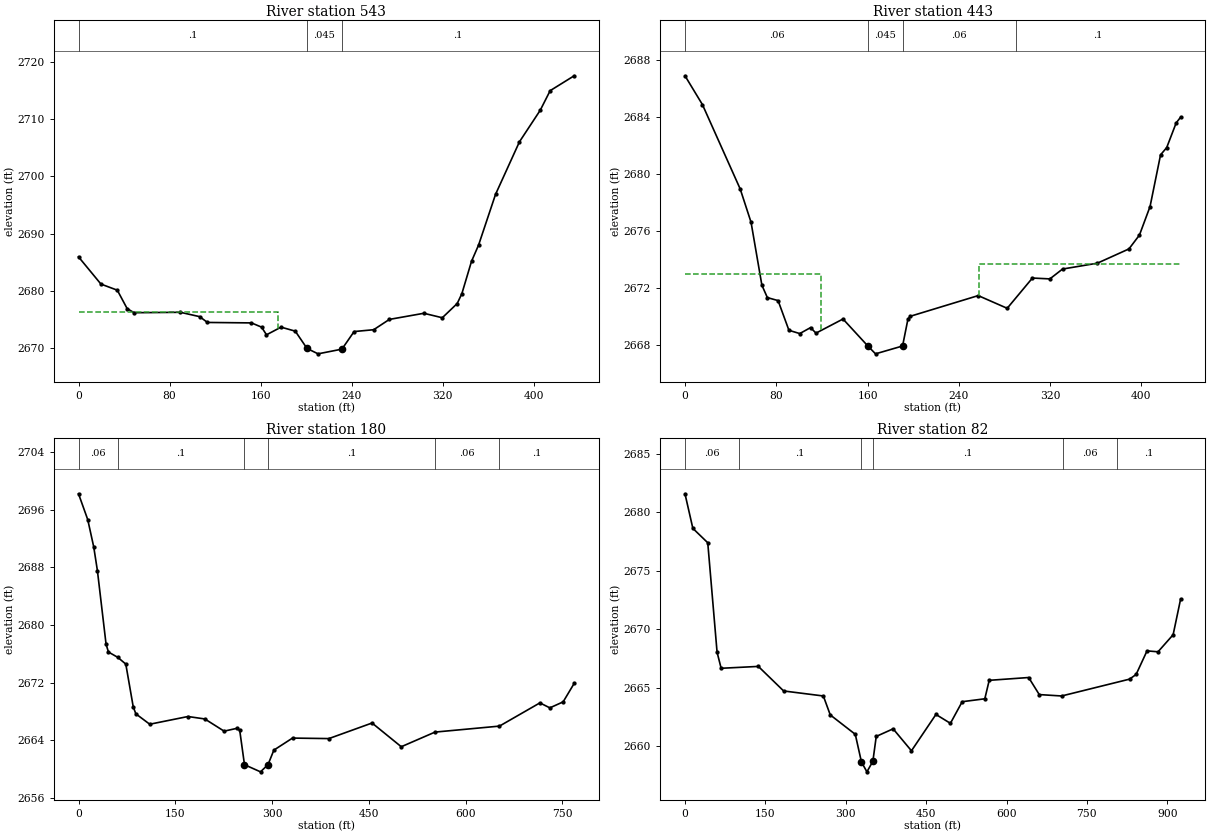
Type RM Length L Ch R = 1 ,543     ,99.9,100.3,100.5
XS GIS Cut Line= 6
2217207.97588872517684.5424501132217243.48422328517659.426798845
2217329.22386036 517705.327816682217374.25882126517721.782898545
2217502.43524842517631.7129767562217541.40781073 517550.30362437
#Sta/Elev= 30
       0 2685.93    19.7 2681.18    34.1 2680.11    42.7 2676.91    48.8 2676.18
    89.6 2676.25   106.5 2675.49   113.3 2674.48     152  2674.4   160.9 2673.66
   165.2 2672.32     178 2673.66   190.5 2672.96   200.8 2669.95   210.5    2669
   231.5 2669.82   242.2 2672.89   259.4 2673.21   273.2 2675.01   303.5 2676.08
   319.7  2675.3   332.8 2677.78   336.9  2679.5   345.4 2685.16   351.6 2687.99
   366.5 2696.84   387.5 2706.01   405.8 2711.53   414.5 2714.94   435.6 2717.54
#Mann= 3 ,0,0
       0      .1       0   200.8    .045       0   231.5      .1       0
#XS Ineff= 2 , 0
          175.49 2676.24
Permanent Ineff=
       F       F
Bank Sta=200.8,231.5
XS Rating Curve= 0 ,0
Exp/Cntr(USF)=0,0
Exp/Cntr=0.3,0.1

Type RM Length L Ch R = 1 ,443     ,257.8,262.8,274.6
XS GIS Cut Line= 3
2217303.29716468517880.7902786672217563.08935509517715.511630522
2217626.31132221517605.919531678
#Sta/Elev= 30
       0 2686.89    15.3 2684.87    48.4 2678.96    57.9 2676.63    67.4 2672.22
    72.2 2671.35    81.6 2671.14    91.1 2669.06   100.6 2668.83   110.1 2669.25
   114.8 2668.86   138.5 2669.85   160.5 2667.94     167 2667.41   190.7 2667.96
   195.4 2669.84   197.4 2670.04     257 2671.49   282.4  2670.6   304.5 2672.72
   319.8 2672.66   330.9 2673.35   361.4 2673.76   389.1 2674.76   398.3 2675.73
   407.6 2677.73   416.8 2681.35   422.2 2681.86   430.5 2683.59   434.4 2683.99
#Mann= 4 ,-1,0
       0     .06       0   160.5    .045       0   190.7     .06       0
     290      .1       0
#XS Ineff= 2 , 0
          119.05    2673  257.75         2673.71
Permanent Ineff=
       F       F
Bank Sta=160.5,190.7
XS Rating Curve= 0 ,0
Exp/Cntr(USF)=0,0
Exp/Cntr=0.3,0.1

Type RM Length L Ch R = 1 ,180     ,101.6,97.2,96.6
XS GIS Cut Line= 5
2217224.75184215517974.1998323142217436.61492096518053.482706671
 2217512.8279317518045.6881942092217575.85403633517982.209646037
2217664.33169915517613.263585461
#Sta/Elev= 30
       0 2698.18    14.3  2694.6    23.6 2690.81    29.3 2687.52    42.7 2677.33
    46.4 2676.24    60.9  2675.5    73.3 2674.57    84.8 2668.65    88.9 2667.67
   110.4 2666.23   169.7  2667.3   195.8 2666.96   225.7 2665.27   245.9 2665.67
   249.9 2665.38  257.27 2660.62   282.1 2659.63293.76582660.631   302.8 2662.64
   331.7 2664.31   388.1 2664.24     455  2666.4   500.3 2663.11   552.6 2665.14
   652.5 2665.97   715.2 2669.19   730.6  2668.5   751.2 2669.33   768.3 2671.89
#Mann= 6 ,-1,0
       0     .06       0    60.9      .1       0  257.27    .045       0
293.7658      .1       0   552.6     .06       0   652.5      .1       0
Bank Sta=257.27,293.7658
XS Rating Curve= 0 ,0
Exp/Cntr(USF)=0,0
Exp/Cntr=0.3,0.1

Type RM Length L Ch R = 1 ,82      ,,,
XS GIS Cut Line= 5
 2217188.1063068518017.4082900382217426.59107182518166.559019607
2217498.97102066518135.7581159972217580.88107162518027.941163268
2217670.69937172517607.853823591
#Sta/Elev= 30
       0 2681.58    14.7 2678.62    42.5 2677.39    59.9 2668.02    67.5 2666.65
   136.9 2666.81   184.1 2664.71   258.2 2664.28   271.1 2662.66   317.8    2661
   329.3 2658.63   339.5 2657.79   350.6 2658.69   356.9 2660.82   388.4 2661.47
   422.6 2659.59   468.3  2662.7   495.3 2661.94   517.3 2663.79   559.5 2664.04
   567.7 2665.62   641.3 2665.86   661.1  2664.4   702.8 2664.28   829.5 2665.72
   841.8 2666.12   862.2 2668.14   882.7 2668.06   910.9 2669.52   924.9 2672.58
#Mann= 6 ,-1,0
       0     .06       0     100      .1       0   329.3    .045       0
   350.6      .1       0  705.35     .06       0  805.35      .1       0
Bank Sta=329.3,350.6
XS Rating Curve= 0 ,0
Exp/Cntr(USF)=0,0
Exp/Cntr=0.3,0.1
LCMann Table=0

Chan Stop Cuts=-1
Use User Specified Reach Order=0
Composite Channel Slope=5